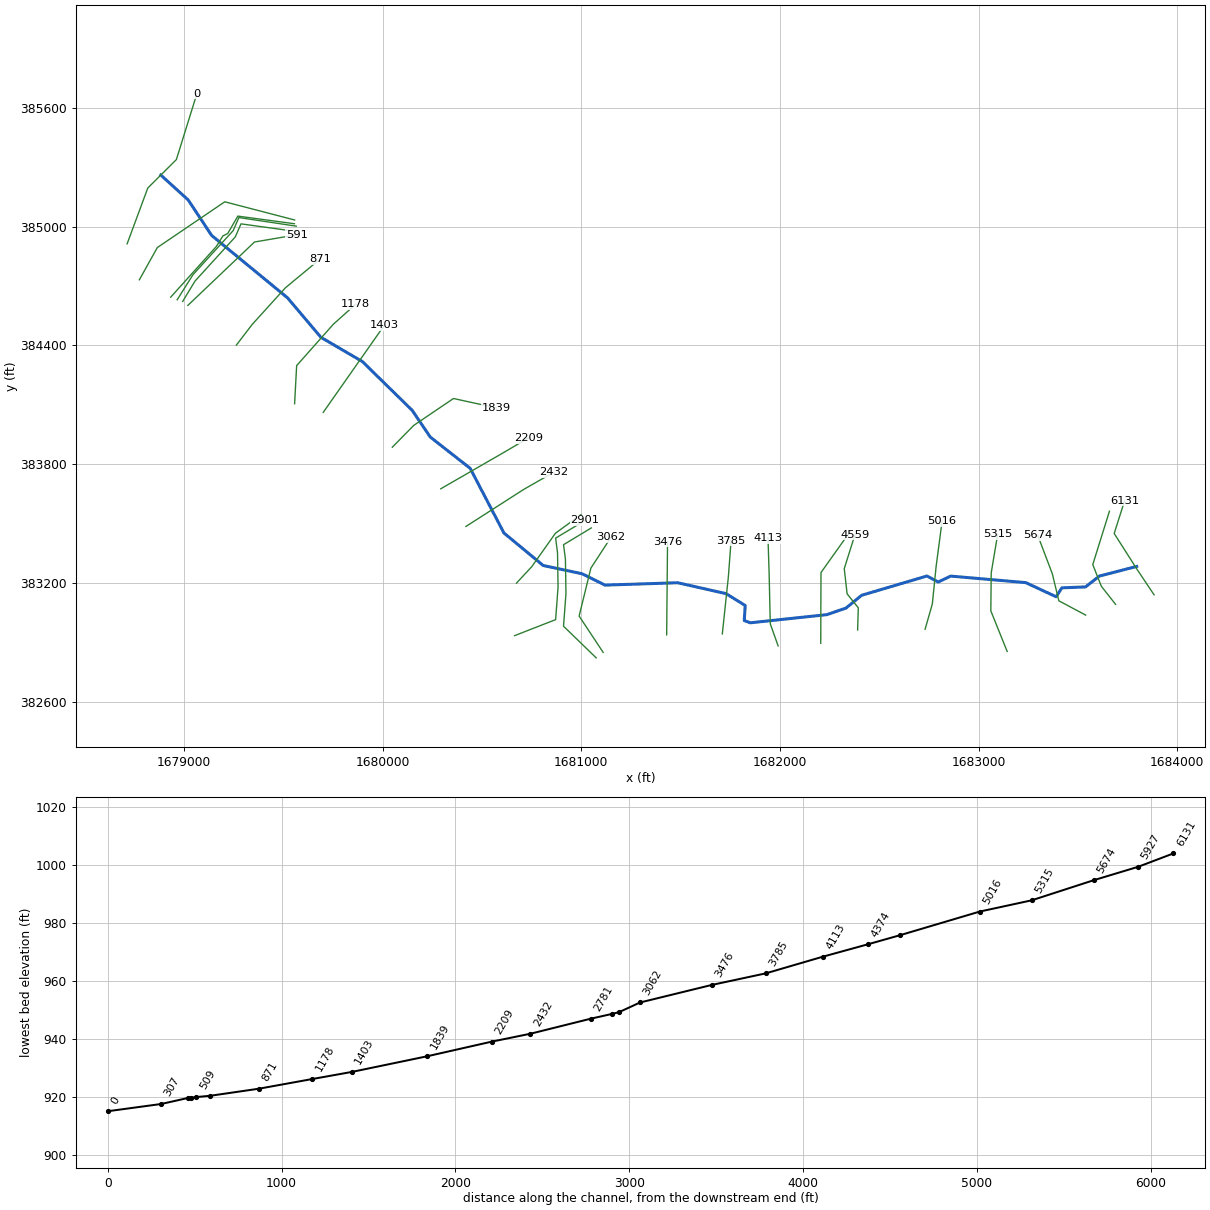
--- NFKFSHNGCK_U.prj (project) ---

Proj Title=NFKFSHNGCK_U
Current Plan=p01
Default Exp/Contr=0,0
English Units
Geom File=g01
Flow File=f01
Plan File=p01
BEGIN DESCRIPTION:
---------- MODELED AS PART OF WVEMD CTP PROGRAM, 2023----------
Stream Name: North Fork Fishing Creek Upper Reach
Flood Zone:  AFH
Wetzel County, WV
HEC-RAS Version: RAS 6.3
Vertical Datum: NAVD88
Projection: NAD 1983 StatePlane West Virginia S FIPS 4702 (US Feet)
Terrain: 1-meter West Virginia FEMA R3 South Central (collected 2018-2020)
Land Use: 2019 NLCD
Hydrologic Method:
WV SIR2010-5033 regression equations
Additional Model Notes:
Model was originally NFKFSHINGCK, but there were 2 dominant flow path issues with WILLEYFK and WILEYFK, so the model was split into three reaches.
There is a coincident peak with WILEYFK; KWSEL tie-in used. DS XS is shared XS with NFKFSHNGCK_M.
END DESCRIPTION:
DSS Export Rating Curves= 0
DSS Export Rating Curve Sorted= 0
DSS Export Volume Flow Curves= 0
DXF OffsetX= 0
DXF OffsetY= 0
DXF ScaleX= 0
DXF ScaleY= 0

--- NFKFSHNGCK_U.p01 (plan) ---

Plan Title=Floodplain
Program Version=6.31
Short Identifier=Floodplain
Geom File=g01
Flow File=f01
Subcritical Flow
K Sum by GR= 0
Std Step Tol= 0.01
Critical Tol= 0.01
Num of Std Step Trials= 20
Max Error Tol= 0.3
Flow Tol Ratio= 0.001
Split Flow NTrial= 30
Split Flow Tol= 0.02
Split Flow Ratio= 0.02
Log Output Level= 0
Friction Slope Method= 1
Unsteady Friction Slope Method= 2
Unsteady Bridges Friction Slope Method= 1
Parabolic Critical Depth
Global Vel Dist= 0 , 0 , 0
Global Log Level= 0
CheckData=True
Encroach Param=-1 ,0,0, 0
Mapping Interval=1HOUR
Computation Time Step Use Courant=        0
Computation Time Step Use Time Series=    0
Computation Time Step Count To Double=0
Computation Time Step Max Doubling=0
Computation Time Step Max Halving=0
Computation Time Step Residence Courant=0
Run HTab= 0
Run UNet= 0
Run Sediment= 0
Run PostProcess= 0
Run WQNet= 0
Run RASMapper= 0
UNET Theta= 0
UNET Theta Warmup= 0
UNET ZTol= 0
UNET ZSATol= 0
UNET MxIter= 0
UNET Max Iter WO Improvement= 0
UNET MaxInSteps= 0
UNET DtIC= 0
UNET DtMin= 0
UNET MaxCRTS= 0
UNET WFStab= 0
UNET SFStab= 0
UNET WFX= 1
UNET SFX= 1
UNET Gravity=32.17405
UNET 1D Methodology=Finite Difference
UNET DSS MLevel= 1
UNET Pardiso=0
UNET DZMax Abort= 0
UNET Use Existing IB Tables= 0
UNET Froude Reduction=False
UNET Froude Limit= 0
UNET Froude Power= 0
UNET D1 Cores= 0
UNET WindReference=Eulerian
UNET WindDragFormulation=Hsu (1988)
UNET D2 Coriolis=0
UNET D2 Cores= 0
UNET D2 Theta= 1
UNET D2 Theta Warmup= 1
UNET D2 Z Tol= 0.01
UNET D2 Volume Tol= 0.01
UNET D2 Max Iterations= 20
UNET D2 Equation= 0
UNET D2 RampUpFraction=0.1
UNET D2 TimeSlices= 1
UNET D2 Turbulence Formulation=Non-Conservative (original)
UNET D2 Eddy Viscosity=0.3
UNET D2 Transverse Eddy Viscosity=0.1
UNET D2 Smagorinsky Mixing=0
UNET D2 BCVolumeCheck=0
UNET D2 Cores=0
UNET D2 SolverType=PARDISO (Direct)
UNET D2 Minimum Iterations= 3
UNET D2 Maximum Iterations= 30
UNET D2 Restart Number= 10
UNET D2 Relaxation Coeff=1.3
UNET D2 SOR Precondition Iterations= 10
UNET D2 ILUT Maximum Fill= 8
UNET D2 ILUT Tolerance=1E-08
UNET D2 Convergence Tolerance=0.00001
UNET D1D2 MaxIter= 0
UNET D1D2 ZTol=0.01
UNET D1D2 QTol=0.1
UNET D1D2 MinQTol=1
Write IC File= 0
Write IC File at Fixed DateTime=0
Write IC File at Sim End=0
Echo Input=False
Echo Parameters=False
Echo Output=False
Write Detailed= 0
HDF Write Warmup=0
HDF Write Time Slices=0
HDF Flush=0
HDF Compression= 1
HDF Chunk Size= 1
HDF Spatial Parts= 1
HDF Use Max Rows=0
HDF Fixed Rows= 1
Calibration Method= 0
Calibration Iterations= 20
Calibration Max Change=0.05
Calibration Tolerance=0.2
Calibration Maximum=1.5
Calibration Minimum=0.5
Calibration Optimization Method= 1
WQ AD Non Conservative
WQ ULTIMATE=-1
WQ Max Comp Step=1HOUR
WQ Output Interval=15MIN
WQ Output Selected Increments= 0
WQ Create Restart=0
WQ Fixed Restart=0
WQ System Summary=0
WQ Write To DSS=0
Sorting and Armoring Iterations= 10
XS Update Threshold= 0.02
Bed Roughness Predictor= 0
Hydraulics Update Threshold= 0.02
Energy Slope Method= 1
Volume Change Method= 1
Sediment Retention Method= 0
Sediment TS Multiplier= 1
Warm Up Method= 0
XS Weighting Method= 0
Number of US Weighted Cross Sections= 1
Number of DS Weighted Cross Sections= 1
Upstream XS Weight=0
Main XS Weight=1
Downstream XS Weight=0
Number of DS XS's Weighted with US Boundary= 1
Upstream Boundary Weight= 1
Weight of XSs Associated with US Boundary= 0
Number of US XS's Weighted with DS Boundary= 1
Downstream Boundary Weight= 0.5
Weight of XSs Associated with DS Boundary= 0.5
Percentile Method= 0
Sediment Output Level= 3
Mass or Volume Output= 0
Output Increment Type= 1
Profile and TS Output Increment= 1
Transport Output Increment 1
XS Output Flag= 0
XS Output Increment= 10
Read HDF5 Sediment Hotstart= 0
Sediment Hotstart Type= 0
Write Gradation File= 0
Read Gradation Hotstart= 0
Write HDF5 File= 1
Write Binary Output= 1
Write DSS Sediment File= 0
DSS Sediment Output Type= 1
SV Curve= 0
Specific Gage Flag= 0
Subcell Erosion Methods= 0
Subcell Deposition Methods= 0
Advection Scheme= 1
Matrix Solver= 0
Implicit Weighting Factor= 1
Maximum Outer Loop Convergence Iterations= 5
Convergence Maximum Absolute= 0.001
Convergence RMSE= 0.0001
Grain Fractions Max Abs Error= 0.001
Max Subgrid Regions= 1
Max Subgrid Length Scale= 3.402823E+38
Initial Layer Thickness= 3.402823E+38
Min Layer Thickness= 3.402823E+38
Max Layer Thickness= 3.402823E+38
Number of Layers= 5

--- NFKFSHNGCK_U.f01 (steady flow) ---

Flow Title=Flow
Program Version=6.31
Number of Profiles= 1
Profile Names=F01pct
River Rch & RM=NFKFSHNGCK_U,Main            ,6131
     517
River Rch & RM=NFKFSHNGCK_U,Main            ,5315
     596
River Rch & RM=NFKFSHNGCK_U,Main            ,2901
     868
River Rch & RM=NFKFSHNGCK_U,Main            ,307
    1680
River Rch & RM=NFKFSHNGCK_U,Main            ,0
    1940
Boundary for River Rch & Prof#=NFKFSHNGCK_U,Main            , 1
Up Type= 0
Dn Type= 1
Dn Known WS=920.6
DSS Import GetInterval= 0
DSS Import GetPeak= 0
DSS Import FillOption= 0

--- NFKFSHNGCK_U.g01 (geometry) ---

Geom Title=Geometry
Program Version=6.31

River Reach=NFKFSHNGCK_U    ,Main
Reach XY= 30
1683796.02107358383283.2607785711683608.46979229 383234.55943816
 1683538.4012249383179.7188164091683419.24869585383175.047091534
1683390.55288445383130.0360055571683237.67899794383201.421740776
1682860.02840927383234.3765303931682796.49074969383204.500875541
1682740.56708936 383234.98628765 1682411.4533384383137.475740785
1682332.41565749383072.6480433641682235.56756297383039.593947547
1681850.68399793382998.4320055171681820.37799795383009.928005532
1681825.25499793383085.8670055631681728.69428302383145.772899185
1681485.48270428383200.810899123 1681119.3565049383188.899203723
1681003.90012244 383246.259277461680808.09199797383287.906005532
1680610.42799796383452.2680055461680440.53453779383778.916866738
1680239.59599793383936.8700055481680149.02599795384071.330005502
1679898.21899794384317.9570055251679689.21299792384440.574005549
1679520.96299795 384640.175005531679138.82999794384955.426005544
1679021.08999793385134.4740055261678883.09609265385260.326913768

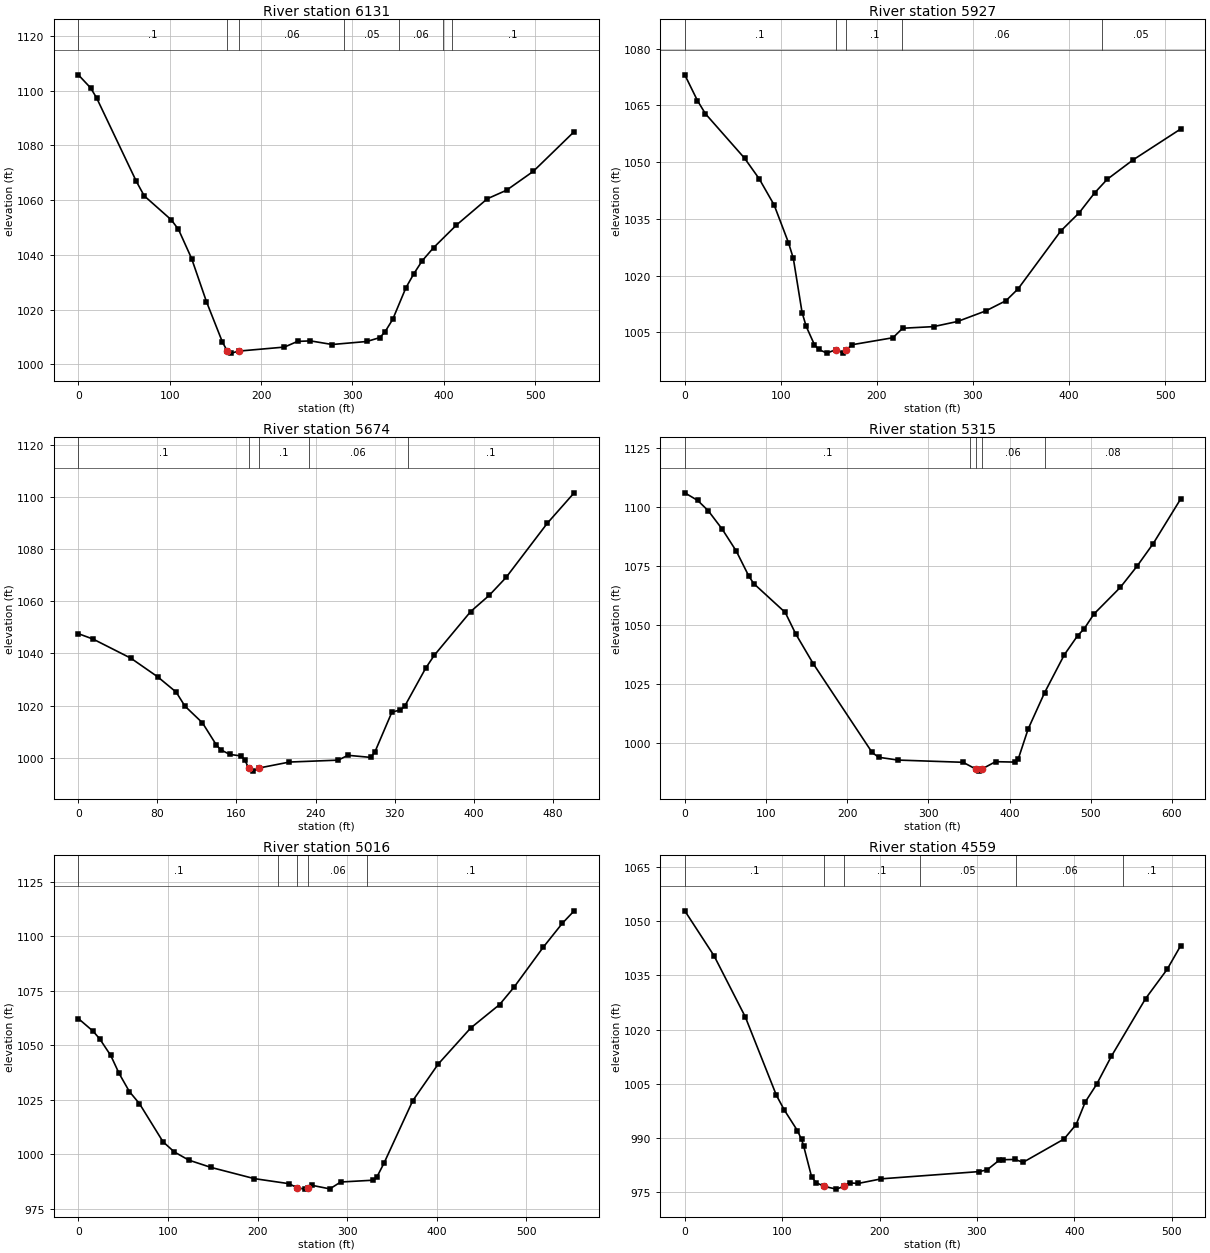
Type RM Length L Ch R = 1 ,6131    ,203.6,204.1,200.9
XS GIS Cut Line= 4
1683883.53795086383139.9383631291683799.84677483 383265.31651373
1683682.74935253383449.6779674751683735.22857486383615.061214377
#Sta/Elev= 30
       0 1105.76    13.4    1101      20 1097.34    63.5 1066.84    72.1 1061.57
   101.7 1052.81   109.6 1049.32     124 1038.67   140.2 1022.96   157.7 1008.18
  163.051004.875   167.4 1004.13  175.851004.878   225.6 1006.34   239.9 1008.41
   254.1  1008.6   277.8 1007.28   315.7 1008.38   329.9 1009.79   335.5 1011.82
   344.1 1016.46   358.6 1028.04   367.3 1033.16   376.3 1037.82   388.9 1042.67
   413.9 1050.91   447.7 1060.51   468.7 1063.62     498 1070.52   542.7 1085.01
#Mann= 7 ,-1,0
       0      .1       0  163.05    .045       0  175.85     .06       0
  290.74     .05       0  350.74     .06       0  399.15     .05       0
  409.15      .1       0
Bank Sta=163.05,175.85
XS Rating Curve= 0 ,0
Exp/Cntr(USF)=0,0
Exp/Cntr=0.3,0.1

Type RM Length L Ch R = 1 ,5927    ,252.4,253.5,251.1
XS GIS Cut Line= 4
1683689.74965564383091.6048411271683617.96210435383183.272022006
1683574.88957357 383292.609984741683658.82578739383562.089408046
#Sta/Elev= 30
       0 1073.08    13.2 1066.25    21.5 1062.78    62.2 1051.04    77.4 1045.61
      93 1038.67   107.9 1028.72     113 1024.53   122.1 1010.23   126.4 1006.54
     135 1001.71   139.3 1000.48   147.9  999.49  157.031000.395   165.1  999.53
  168.271000.393   174.3 1001.72   216.7 1003.56   226.8 1006.07     259  1006.5
   284.1 1007.87   313.5 1010.67   334.4 1013.36     347 1016.49   391.4 1031.78
   410.6  1036.6   426.6 1041.84   439.8 1045.46   466.7 1050.59   516.2 1058.75
#Mann= 5 ,-1,0
       0      .1       0  157.03    .045       0  168.27      .1       0
  226.43     .06       0  433.95     .05       0
Bank Sta=157.03,168.27
XS Rating Curve= 0 ,0
Exp/Cntr(USF)=0,0
Exp/Cntr=0.3,0.1

Type RM Length L Ch R = 1 ,5674    ,357.9,358.2,354.5
XS GIS Cut Line= 4
1683539.03405756383037.4774409641683404.04891838383109.742212443
1683371.32524828383246.0908378761683297.69699054383441.069372245
#Sta/Elev= 30
       0 1047.59      15  1045.5    53.2 1038.18    80.4 1031.02      99 1025.19
   107.8 1019.85   125.6 1013.41   139.4 1005.09     144 1003.13   153.1 1001.32
   164.2 1000.76   168.3  999.29  172.31 996.091   176.6  994.91  182.76 996.095
   213.6  998.39   262.9  999.12   272.8 1000.97   295.9 1000.17   300.2 1002.37
   317.3 1017.53   325.9 1018.35   330.2 1019.75   351.5 1034.39   360.1 1039.27
     397 1056.07   415.7 1062.25   432.8 1069.12   474.6 1089.94   501.7 1101.56
#Mann= 5 ,-1,0
       0      .1       0  172.31    .045       0  182.76      .1       0
  233.11     .06       0  333.33      .1       0
Bank Sta=172.31,182.76
XS Rating Curve= 0 ,0
Exp/Cntr(USF)=0,0
Exp/Cntr=0.3,0.1

Type RM Length L Ch R = 1 ,5315    ,298.6,298.9,297.2
XS GIS Cut Line= 4
1683143.96755281382853.7385407791683061.70846051 383058.73407516
1683063.68379665 383251.003962611683096.19541258383445.770215237
#Sta/Elev= 30
       0 1106.06    15.9 1102.82    28.9 1098.45    46.1 1090.63    63.4 1081.34
    78.9 1070.67    84.9 1067.54   123.7 1055.28   136.6 1046.19   158.2 1033.53
   230.7  995.86   238.7  993.83   262.7  992.64   342.7   991.7   358.4 988.823
   362.7  987.95   365.8  988.83   382.7  991.96   406.7  991.78   410.7  993.16
   422.8 1005.81   443.1 1021.26   467.4 1037.35   483.7  1045.4   491.8 1048.36
   503.9 1054.65   536.4 1065.96   556.7 1074.82   576.9 1084.55   610.6 1103.42
#Mann= 5 ,-1,0
       0      .1       0  350.88     .06       0   358.4    .045       0
   365.8     .06       0  443.16     .08       0
Bank Sta=358.4,365.8
XS Rating Curve= 0 ,0
Exp/Cntr(USF)=0,0
Exp/Cntr=0.3,0.1

Type RM Length L Ch R = 1 ,5016    ,449.3,457.9,460.7
XS GIS Cut Line= 4
1682730.65280477 382965.696885431682767.22328594383093.706882097
1682786.09202851 383281.319386861682816.23598261383511.075868458
#Sta/Elev= 30
       0 1062.23    16.4 1056.46    23.8 1052.95    36.2  1045.3    45.5 1037.07
      57 1028.76    68.2 1023.25    94.5 1005.78     107 1001.14   123.2  997.38
     148  994.03   196.3  988.89   235.2  986.56  243.96  984.74   252.6  984.07
   256.6  984.74   260.6  985.83   280.7  984.18   292.8  987.33     329  988.16
     333  989.45   341.1  995.92   373.3 1024.62   401.6 1041.34   437.9 1057.89
   470.2 1068.65   486.3  1076.6   518.9 1094.91   540.3 1105.92   553.4 1111.59
#Mann= 5 ,-1,0
       0      .1       0  223.13     .06       0  243.96    .045       0
   256.6     .06       0  321.69      .1       0
Bank Sta=243.96,256.6
XS Rating Curve= 0 ,0
Exp/Cntr(USF)=0,0
Exp/Cntr=0.3,0.1

Type RM Length L Ch R = 1 ,4559    ,189.1,184.6,178.4
XS GIS Cut Line= 5
1682391.14438194382962.4412207541682394.47182469  383074.1687986
1682338.22965288383144.687489583 1682323.7997415383271.871714854
1682377.37883461383442.910278413
#Sta/Elev= 30
       0 1052.83    30.1 1040.38    62.1 1023.54    94.1 1001.84   102.1  997.83
   115.6  992.12   119.9  989.67     122   987.9   130.2  979.35   134.8  977.73
  143.17976.6815   155.7  975.93  163.08976.6815   169.2  977.67   177.8  977.49
     202  978.78   302.5  980.78   310.5  981.26   322.6  983.86   326.6  984.06
   339.1  984.13   347.4  983.34   389.4  989.76   401.9  993.78   411.3 1000.03
   422.9 1004.87   438.1 1012.65   473.2 1028.57   495.3 1036.64   509.2 1043.17
#Mann= 6 ,-1,0
       0      .1       0  143.17    .045       0  163.08      .1       0
  241.98     .05       0  339.98     .06       0  449.98      .1       0
Bank Sta=143.17,163.08
XS Rating Curve= 0 ,0
Exp/Cntr(USF)=0,0
Exp/Cntr=0.3,0.1

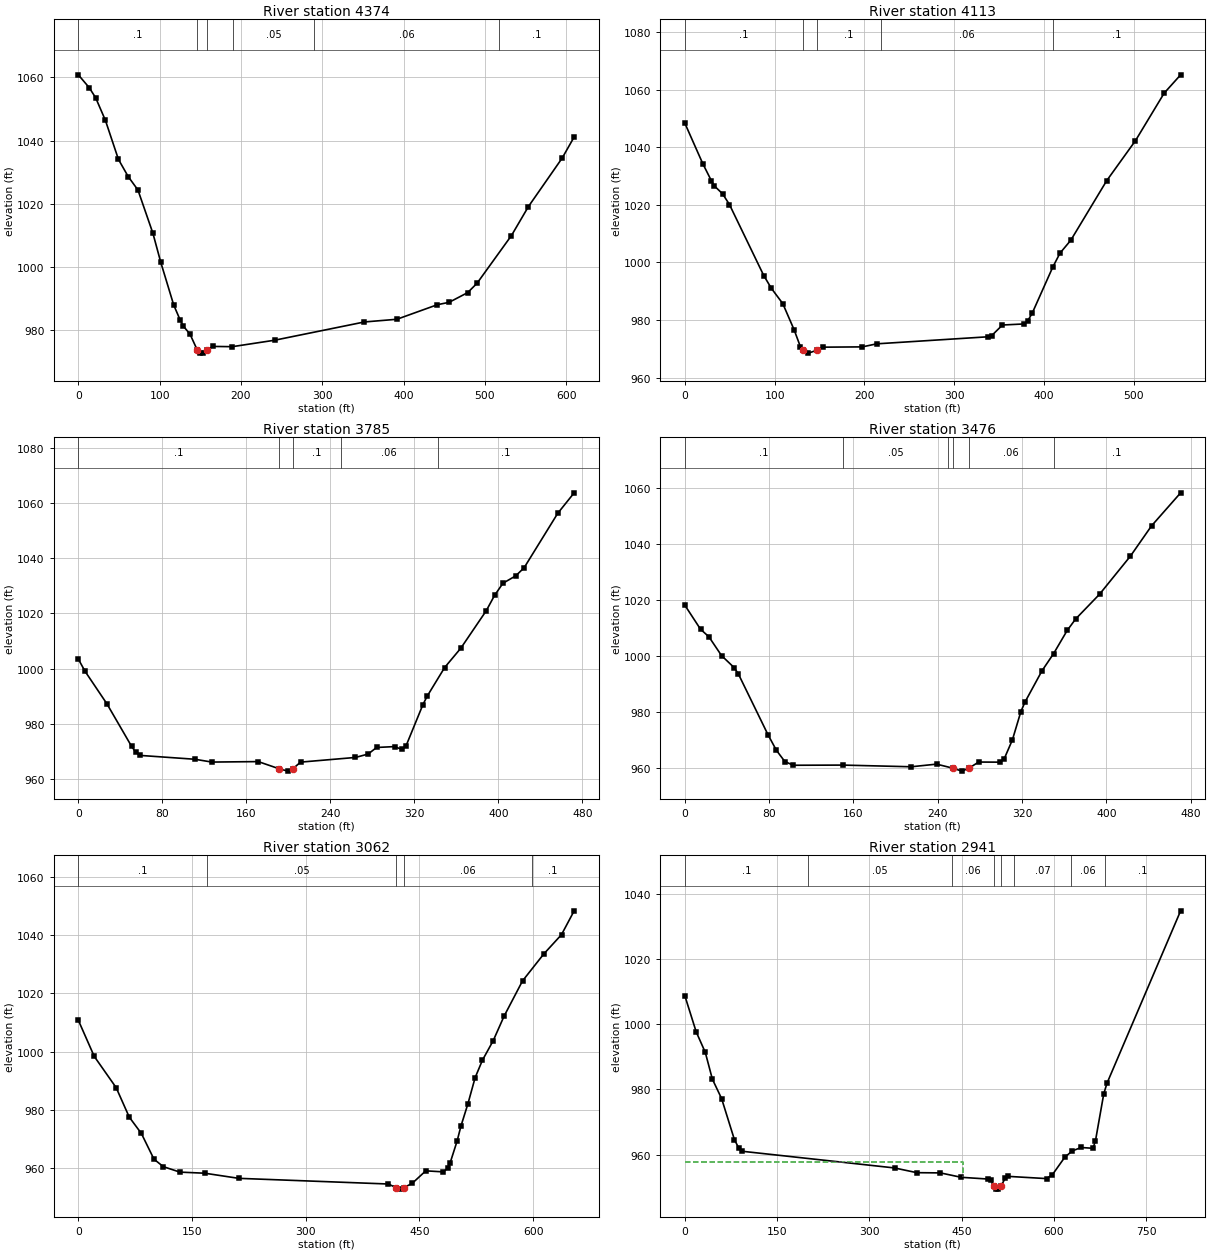
Type RM Length L Ch R = 1 ,4374    ,260.4,261.3,260
XS GIS Cut Line= 3
1682205.43004582382895.2263624171682206.65718345383252.323412426
1682352.68656129383458.482534081
#Sta/Elev= 30
       0 1060.84    13.3 1056.81    21.3 1053.59    33.3 1046.43    49.3  1034.1
    61.3 1028.66    73.3  1024.4    91.7 1010.72   101.3 1001.59   117.3  988.01
   125.3  983.23   129.3  981.29   137.3  978.81   146.1973.8666   149.3  972.98
   153.3   972.8   158.6 973.867   165.3  974.92   189.3  974.84   241.3  976.88
   351.8  982.66   391.7  983.51   441.5  988.12   455.9  988.87   478.8  991.95
   490.3  994.91   532.6    1010   553.5 1019.18   594.9 1034.48   609.7 1041.18
#Mann= 6 ,-1,0
       0      .1       0   146.1    .045       0   158.6      .1       0
     190     .05       0     290     .06       0   517.1      .1       0
Bank Sta=146.1,158.6
XS Rating Curve= 0 ,0
Exp/Cntr(USF)=0,0
Exp/Cntr=0.3,0.1

Type RM Length L Ch R = 1 ,4113    ,319.3,327.4,315.8
XS GIS Cut Line= 4
1681990.96607487 382881.683281161681951.37844929382993.188815534
1681945.67985558383244.6492581551681939.94011296383426.792683361
#Sta/Elev= 30
       0 1048.43      20 1034.34    29.5 1028.45    32.7 1026.65    42.1 1023.84
    49.7 1020.13    87.9  995.46    96.4     991   109.1   985.7   121.7  976.62
   128.7  970.73  131.74   969.5   137.7  968.49   147.1   969.5   153.7  970.56
   197.7  970.66   213.7  971.72   337.7  974.17   341.7  974.57   353.7  978.26
   377.7  978.63   381.7  979.63   386.8  982.34   409.8  998.42   417.8 1003.24
   429.8 1007.71   469.8 1028.42   501.8 1042.31   533.8 1058.84   552.1 1065.19
#Mann= 5 ,-1,0
       0      .1       0  131.74    .045       0   147.1      .1       0
  218.32     .06       0  409.85      .1       0
Bank Sta=131.74,147.1
XS Rating Curve= 0 ,0
Exp/Cntr(USF)=0,0
Exp/Cntr=0.3,0.1

Type RM Length L Ch R = 1 ,3785    ,308.6,309.6,310.7
XS GIS Cut Line= 3
 1681709.8859718382942.1429162381681740.57745472383232.562913319
 1681753.9384035383412.125987119
#Sta/Elev= 30
       0 1003.44     6.4  999.01    27.2  987.21    50.7  971.76    54.7  969.59
    58.7  968.47     111  967.07   127.1  966.05   171.3  966.22  191.27963.6069
   199.5  962.76   204.3  963.63   211.6  966.03   263.9  967.73   275.9  968.96
     284  971.35   301.2  971.67   308.1  970.62   312.1     972   328.1  986.91
   332.1  989.94   348.8 1000.39   364.2 1007.41   388.3 1020.95   396.3 1026.56
   404.3 1030.99   416.4 1033.66   424.4 1036.58   456.5  1056.4   472.1 1063.82
#Mann= 5 ,-1,0
       0      .1       0  191.27    .045       0   204.3      .1       0
     250     .06       0  342.04      .1       0
Bank Sta=191.27,204.3
XS Rating Curve= 0 ,0
Exp/Cntr(USF)=0,0
Exp/Cntr=0.3,0.1

Type RM Length L Ch R = 1 ,3476    ,413.3,413.3,411.4
XS GIS Cut Line= 2
1681429.76619762382937.6444339271681434.18389309383408.129000846
#Sta/Elev= 30
       0 1018.16    14.9 1009.55    22.9 1006.82    34.9 1000.09    46.9  995.78
    50.9  993.49    78.9  971.84    86.9  966.24    94.9  962.22   102.9  960.88
     150  960.94   214.9  960.34   238.9  961.28   254.9  959.79   262.9  958.78
  269.33959.7792   278.9  962.03   298.9  961.99   302.9  963.01   310.9     970
   318.9  980.07   322.9  983.55   338.9  994.64     350 1000.84   362.9 1009.13
   370.9 1013.21   393.6 1022.07   422.9 1035.71   442.9 1046.52   470.5 1058.33
#Mann= 6 ,-1,0
       0      .1       0     150     .05       0     250     .06       0
   254.9    .045       0  269.33     .06       0     350      .1       0
Bank Sta=254.9,269.33
XS Rating Curve= 0 ,0
Exp/Cntr(USF)=0,0
Exp/Cntr=0.3,0.1

Type RM Length L Ch R = 1 ,3062    ,119.4,121.2,122.4
XS GIS Cut Line= 4
1681109.91062234 382849.221777421680989.05860024383032.449395222
1681048.19526702 383274.622172591681149.19857083383430.091582755
#Sta/Elev= 30
       0 1010.79      21  998.36    49.9  987.62    67.2  977.48    83.2  971.85
    99.8  963.01   112.2  960.44     134  958.57   166.9  958.19   211.6  956.43
     409  954.48  419.26953.2374   425.5  952.72   429.6  953.26   440.5   954.7
   458.4  959.01   481.7  958.65   487.5     960   490.7  961.86   499.7   969.2
   504.8  974.38     514  982.04   523.5  991.02   533.1  997.01   547.4 1003.77
   561.7 1012.17   586.1 1024.33   614.2  1033.6   637.5 1040.22   654.2 1048.41
#Mann= 5 ,-1,0
       0      .1       0     170     .05       0  419.26    .045       0
   429.6     .06       0  598.78      .1       0
Bank Sta=419.26,429.6
XS Rating Curve= 0 ,0
Exp/Cntr(USF)=0,0
Exp/Cntr=0.3,0.1

Type RM Length L Ch R = 1 ,2941    ,39.5,40.6,40.7
XS GIS Cut Line= 6
1681075.01706829 382821.301122261680910.52307022 382981.24577063
1680922.79444651383146.2276074031680920.06747401383319.390361703
1680910.52307022383393.0186194371681050.40901941383477.770315293
#Sta/Elev= 30
       0 1008.78    18.5  997.66    33.3  991.35    44.8  983.14    59.8  977.18
    80.7  964.53    87.7  962.01    93.3     961     341  955.88   377.1  954.43
   415.5  954.36   449.2  953.01   493.2  952.47   497.2  952.16  502.55 950.486
   505.2  949.44   508.3  949.38  514.44950.4858   521.2  952.89   525.2   953.3
     588  952.61   597.6  953.84   617.6  959.16   629.7   961.1   644.2  962.16
   663.5  961.91   667.5  964.23     681  978.67   686.3  981.92   805.9  1034.8
#Mann= 8 ,-1,0
       0      .1       0     200     .05       0  434.87     .06       0
  502.55    .045       0  514.44     .06       0  534.87     .07       0
  628.06     .06       0   682.3      .1       0
#XS Ineff= 2 , 0
          452.44  957.59
Permanent Ineff=
       F       F
Bank Sta=502.55,514.44
XS Rating Curve= 0 ,0
Exp/Cntr(USF)=0,0
Exp/Cntr=0.3,0.1

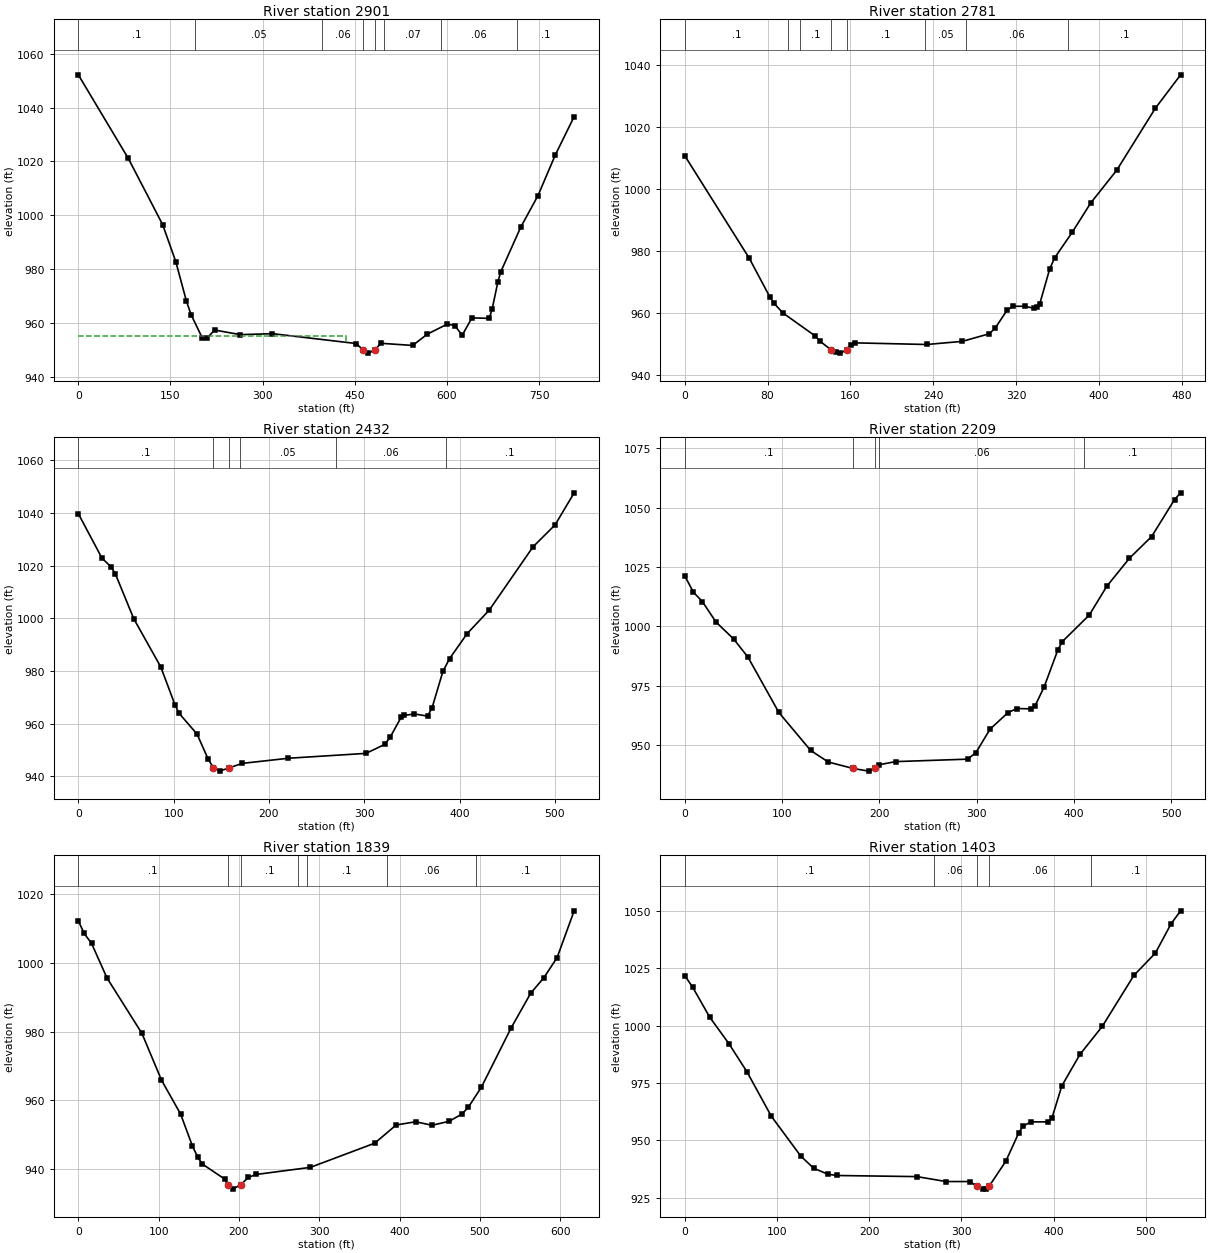
Type RM Length L Ch R = 1 ,2901    ,126.2,119.9,114.8
XS GIS Cut Line= 6
1680664.36378638382933.580359936 1680870.7380495383014.442805554
1680883.00942578383179.4246423281680880.28245328383352.587396628
 1680870.7380495383426.2156543621681018.59473616383515.315025209
#Sta/Elev= 30
       0 1052.14    81.4 1021.07   137.2  996.53   158.7  982.71   175.9  968.12
   183.5  963.08   201.6  954.48   210.2  954.49   221.7  957.35   263.9  955.63
     316     956   452.2  952.34  463.34950.0194   472.2  948.77   483.2  950.02
   492.2  952.43   544.2  951.62   568.3  955.85   600.6  959.54   612.7  959.03
   624.8  955.43   640.8  961.87   668.8  961.68   673.5  965.01   682.8  975.08
   687.5  978.91   720.2  995.58   748.2 1007.27   776.2 1022.27   807.1 1036.63
#Mann= 8 ,-1,0
       0      .1       0     190     .05       0  397.09     .06       0
  463.34    .045       0   483.2     .06       0  497.09     .07       0
  590.27     .06       0  714.52      .1       0
#XS Ineff= 2 , 0
           435.8   955.1
Permanent Ineff=
       F       F
Bank Sta=463.34,483.2
XS Rating Curve= 0 ,0
Exp/Cntr(USF)=0,0
Exp/Cntr=0.3,0.1

Type RM Length L Ch R = 1 ,2781    ,350.5,348.8,344.2
XS GIS Cut Line= 4
1680673.60771293383198.9862142051680749.69202527383280.867426534
1680869.97770002383451.1513636781680998.23411225383544.626375983
#Sta/Elev= 30
       0 1010.72    62.2  977.76    82.1  965.29      86  963.27    94.9  960.06
   126.1  952.66   130.5  951.02  141.16948.2599   145.7  947.41   150.3  947.16
  156.66948.2589   160.3  949.91   164.9  950.46   233.8  949.94   268.1  950.95
   294.1  953.39   299.8  955.19   311.3  960.96     317  962.25   328.5  962.25
   337.7  961.57     340  961.88     343  963.14   352.6  974.37   357.5  977.94
   374.3  986.08   392.2  995.54   417.3 1006.07   454.5 1025.98     479 1036.78
#Mann= 8 ,-1,0
       0      .1       0     100     .06       0  111.77      .1       0
  141.16    .045       0  156.66      .1       0  231.77     .05       0
  271.77     .06       0  370.26      .1       0
Bank Sta=141.16,156.66
XS Rating Curve= 0 ,0
Exp/Cntr(USF)=0,0
Exp/Cntr=0.3,0.1

Type RM Length L Ch R = 1 ,2432    ,222.7,222.8,222.5
XS GIS Cut Line= 3
1680419.28559156383485.2359475361680709.88757607383672.147670055
1680861.43564932383759.139335933
#Sta/Elev= 30
       0 1039.69    24.8 1022.82    34.3 1019.53      39 1016.73    58.1  999.87
    86.6  981.45   101.4  967.13   105.6  963.96   124.6     956   136.1  946.61
  141.77943.2202   148.4  941.95  158.39 943.221   172.2   944.9   220.5  946.84
   301.9  948.69   321.4  952.07   327.2  954.81   338.7  962.37   341.6  963.08
   352.7  963.66   366.5  962.84   371.2  966.01   382.6  979.85   389.6  984.68
     408  994.16   431.1 1003.05   477.2 1027.14   500.3 1035.45   520.3 1047.62
#Mann= 6 ,-1,0
       0      .1       0  141.77    .045       0  158.39      .1       0
     170     .05       0     270     .06       0  385.52      .1       0
Bank Sta=141.77,158.39
XS Rating Curve= 0 ,0
Exp/Cntr(USF)=0,0
Exp/Cntr=0.3,0.1

Type RM Length L Ch R = 1 ,2209    ,367.5,370.2,370.4
XS GIS Cut Line= 3
1680292.41535472383675.4609416531680596.13191787383851.064336348
1680733.08047726383931.687278566
#Sta/Elev= 30
       0 1021.23     8.9 1014.38    18.1 1010.47      32  1001.9    50.3  994.71
      65  987.07    96.7  963.86   129.4   947.9   147.5  943.04  173.11940.3334
   189.1  939.22   195.2940.3339   199.7   941.9   216.8  943.22   290.7  944.25
   299.2  946.96   313.8  956.85   332.3  963.85   341.6  965.53   355.4  965.39
   360.1  966.69   369.4  974.61   383.3  989.95   387.9  993.57   415.8 1004.81
   433.7 1016.84   457.1 1028.69   479.9 1037.81   503.5 1053.36   509.7 1056.17
#Mann= 5 ,-1,0
       0      .1       0  173.11    .045       0   195.2     .05       0
     200     .06       0  410.83      .1       0
Bank Sta=173.11,195.2
XS Rating Curve= 0 ,0
Exp/Cntr(USF)=0,0
Exp/Cntr=0.3,0.1

Type RM Length L Ch R = 1 ,1839    ,433.4,435.9,438.7
XS GIS Cut Line= 4
1680048.65304736383885.659137357 1680156.5712192383995.743862795
1680356.47193895384131.5879983131680572.93901669384084.097772075
#Sta/Elev= 30
       0 1012.22     7.3 1008.53    16.4 1005.69    35.6  995.64    79.2  979.48
   103.5  965.92   127.3  956.05   142.1  946.73   148.7   943.5   154.4  941.49
   182.6  937.06  186.57  935.52   192.3  934.19  202.62935.5194   211.6  937.58
   221.3  938.45     289  940.52   369.1  947.55   395.8  952.84   420.1  953.78
   440.5  952.76   461.9  953.92   477.4  955.97   485.6  957.96     502  963.85
   538.8  980.98   563.4  991.17   579.8  995.67   596.3 1001.54   617.5 1015.12
#Mann= 7 ,-1,0
       0      .1       0  186.57    .045       0  202.62      .1       0
  274.16     .05       0  284.16      .1       0  384.16     .06       0
  495.85      .1       0
Bank Sta=186.57,202.62
XS Rating Curve= 0 ,0
Exp/Cntr(USF)=0,0
Exp/Cntr=0.3,0.1

Type RM Length L Ch R = 1 ,1403    ,225.6,225.1,223.2
XS GIS Cut Line= 2
1679700.64350046384061.4042295511680008.77775908384502.069352087
#Sta/Elev= 30
       0 1021.77     8.7  1016.6      27 1003.68    47.8  992.14    67.3  979.95
    93.8  960.53   125.8  943.14   139.7  937.88   155.1  935.26   164.9   934.7
   251.8  934.21   283.4  932.06   309.2  932.06  316.63930.0341   323.6  928.76
   326.4  928.81  330.04930.0348   348.1  940.88     362  953.13   366.7  956.17
   375.3  958.06   394.3  958.05   398.3  959.92   408.9  973.77   428.5  987.43
   452.8  999.69     487 1021.85   510.3 1031.57   527.5 1044.45   537.7 1049.99
#Mann= 5 ,-1,0
       0      .1       0     270     .06       0  316.63    .045       0
  330.04     .06       0     440      .1       0
Bank Sta=316.63,330.04
XS Rating Curve= 0 ,0
Exp/Cntr(USF)=0,0
Exp/Cntr=0.3,0.1

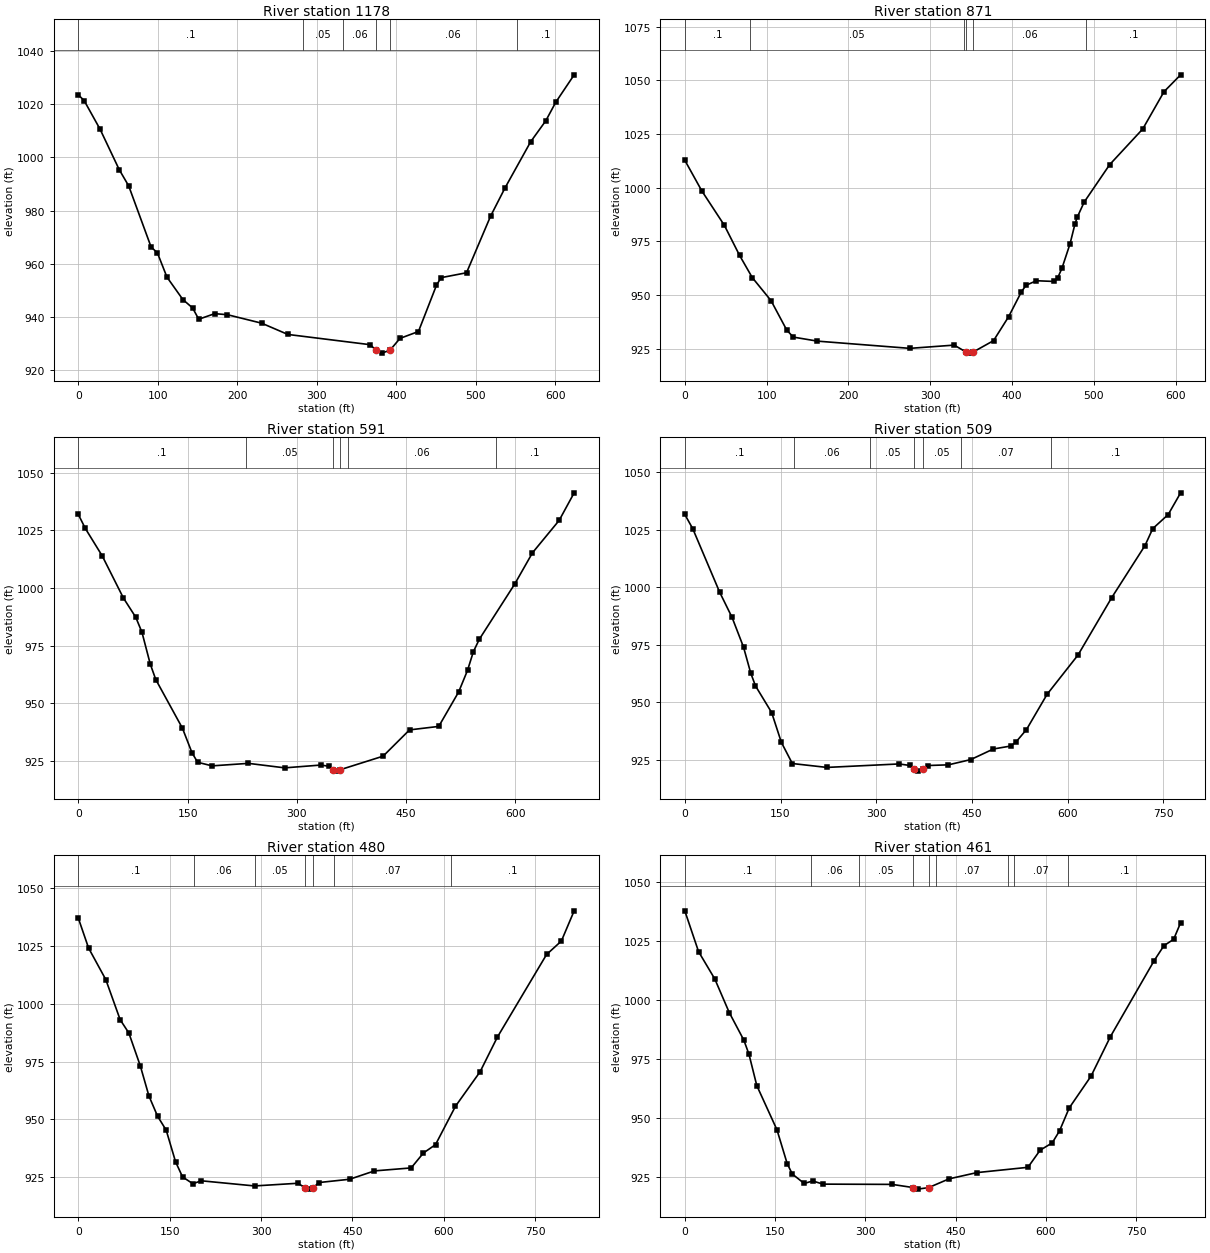
Type RM Length L Ch R = 1 ,1178    ,307.6,307.4,306.3
XS GIS Cut Line= 4
1679556.63192563 384105.213819951679567.00821267384297.750936876
 1679751.4469983384506.4870475511679864.77181629384608.400958697
#Sta/Elev= 30
       0 1023.52     7.3 1021.36    27.4 1010.56    51.4   995.4    63.4  989.23
    91.5   966.3    99.5  964.05   111.5  954.93   131.5  946.51   143.8  943.32
   151.5  939.09   171.6   941.2   187.6  940.79   230.7   937.6   263.6  933.37
   367.3  929.51  374.45927.4275   381.8  926.34  392.07927.4285   404.7  931.89
   427.9  934.47   450.6  951.89   456.3  954.73   488.4  956.58   518.6  977.84
   536.8   988.5   569.1 1005.88   588.1 1013.76   600.7 1020.76   623.8 1031.05
#Mann= 6 ,-1,0
       0      .1       0  282.82     .05       0  332.82     .06       0
  374.45    .045       0  392.07     .06       0  551.36      .1       0
Bank Sta=374.45,392.07
XS Rating Curve= 0 ,0
Exp/Cntr(USF)=0,0
Exp/Cntr=0.3,0.1

Type RM Length L Ch R = 1 ,871     ,279.9,279.8,279.2
XS GIS Cut Line= 4
1679263.51926037384401.4539012671679343.02327444384505.566300643
 1679510.5495898384691.075666804 1679683.7547633384834.940073214
#Sta/Elev= 30
       0 1012.78    20.8   998.5    48.3  982.52    66.9  968.53    82.5  958.15
   105.4  947.44   124.7  933.68   132.6  930.46   162.2  928.58   275.1  925.22
   329.3  926.73  343.82  923.51   349.1     923  352.48  923.51   377.4  928.81
   395.8  939.92   411.5  951.55   417.2  954.59   429.8  956.69   451.3  956.36
   455.8     958     461  962.46   470.9  973.87   477.1  983.32   479.7  986.23
   488.2  993.29   519.4 1010.74   559.8 1027.33   585.8 1044.68   606.1 1052.52
#Mann= 6 ,-1,0
       0      .1       0      80     .05       0     341     .06       0
  343.82    .045       0  352.48     .06       0  490.95      .1       0
Bank Sta=343.82,352.48
XS Rating Curve= 0 ,0
Exp/Cntr(USF)=0,0
Exp/Cntr=0.3,0.1

Type RM Length L Ch R = 1 ,591     ,81.1,81.5,82.1
XS GIS Cut Line= 3
 1679019.2029309384601.887181097 1679354.6716802384922.148013761
1679568.47709642384958.825930351
#Sta/Elev= 30
       0 1031.89     9.6 1025.84    32.8 1013.93    61.9  995.65    78.9  987.29
    87.4  980.74    98.7  967.06   106.3   960.3   142.9  939.19   156.1  928.49
   163.8   924.4   183.6  922.84   233.5  923.93   283.3  921.98   333.1   923.2
   344.1  922.66   349.7  921.12   355.2  920.56     359  921.12   418.4  927.05
   454.7  938.45   494.8  939.96   522.1  954.89   534.3  964.28   542.4  972.42
   550.5  977.77   599.2 1001.77   623.5 1015.29   660.1 1029.33   680.7 1041.29
#Mann= 6 ,-1,0
       0      .1       0     230     .05       0   349.7    .045       0
     359     .05       0     370     .06       0   573.8      .1       0
Bank Sta=349.7,359
XS Rating Curve= 0 ,0
Exp/Cntr(USF)=0,0
Exp/Cntr=0.3,0.1

Type RM Length L Ch R = 1 ,509     ,29.2,29.3,29.2
XS GIS Cut Line= 5
1678993.10624826384621.8092670341679055.70292369 384725.31432595
1679258.18722402384948.192516829 1679286.8036022   385013.841855
1679567.42688926384974.954587593
#Sta/Elev= 30
       0 1031.58    12.5 1025.37    54.6  997.84    74.1  986.85      92  973.99
   103.2  962.81   110.7  957.16   136.1  945.56   151.3  932.62   168.5  923.41
   222.6  921.72   335.9  923.23   352.3  922.58   359.5  920.86   365.5  920.11
   372.7  920.85   381.2  922.55   413.1  922.84   448.1  925.12   483.5  929.72
   511.2  931.03   519.3  932.87   535.4  938.14   567.7  953.45   616.2  970.53
   668.7  995.32   721.2 1018.09   733.3 1025.42   757.5 1031.53     777 1040.97
#Mann= 7 ,-1,0
       0      .1       0  170.96     .06       0  290.96     .05       0
   359.5    .045       0   372.7     .05       0  432.08     .07       0
   573.7      .1       0
Bank Sta=359.5,372.7
XS Rating Curve= 0 ,0
Exp/Cntr(USF)=0,0
Exp/Cntr=0.3,0.1

Type RM Length L Ch R = 1 ,480     ,19.1,19.2,21.5
XS GIS Cut Line= 5
1678965.54319293384630.3482594911679045.13695165384757.112485025
1679247.62125198384979.9906759041679276.23763016385045.640014075
 1679564.9121672385002.279830011
#Sta/Elev= 30
       0 1037.02    16.8 1024.14    45.1 1010.48    68.7  993.13    82.9  987.42
   101.8  973.17   115.9   960.2   130.1  951.43   144.3  945.37   159.7  931.69
   171.2  925.16   188.2  922.21   201.7   923.5   289.4  921.27   360.9  922.43
   372.3  920.42   380.2  919.89  385.55 920.412   394.9  922.73   445.6  924.16
   486.3  927.77   546.6  929.06   566.8  935.53   586.6  939.12   619.4  955.72
   659.8  970.63   688.1  985.56     769 1021.33   793.3 1027.15   814.3 1040.21
#Mann= 7 ,-1,0
       0      .1       0  189.68     .06       0  289.68     .05       0
   372.3    .045       0  385.55     .05       0  419.68     .07       0
  612.42      .1       0
Bank Sta=372.3,385.55
XS Rating Curve= 0 ,0
Exp/Cntr(USF)=0,0
Exp/Cntr=0.3,0.1

Type RM Length L Ch R = 1 ,461     ,155.8,153.3,149.5
XS GIS Cut Line= 6
1678932.86002446384643.4298409491679162.98590945384899.923275319
1679195.78976941384953.1701204681679220.03610068384965.055576974
1679270.90585453385053.0079551221679555.68139242385014.499076041
#Sta/Elev= 30
       0 1037.83    22.9 1020.51    49.9 1008.91    73.9  994.68    98.2  982.95
   106.7  976.96   119.7  963.68   153.2  944.95   170.2   930.6   178.7  926.19
   198.5  922.18   212.7  923.24   229.7   921.9   344.6  921.79   379.6  920.44
     387  919.78   405.2  920.41   439.3  924.14   485.5  926.79   570.4  929.03
   590.6  936.28   610.8  939.41   622.9  944.49     639  954.21   675.3  967.72
   707.6  984.52   780.3 1016.74   796.4 1023.04   812.6 1025.75   824.2 1032.79
#Mann= 9 ,-1,0
       0      .1       0     210     .06       0     290     .05       0
   379.6    .045       0   405.2     .05       0  418.27     .07       0
  536.88      .1       0  546.88     .07       0  636.88      .1       0
Bank Sta=379.6,405.2
XS Rating Curve= 0 ,0
Exp/Cntr(USF)=0,0
Exp/Cntr=0.3,0.1

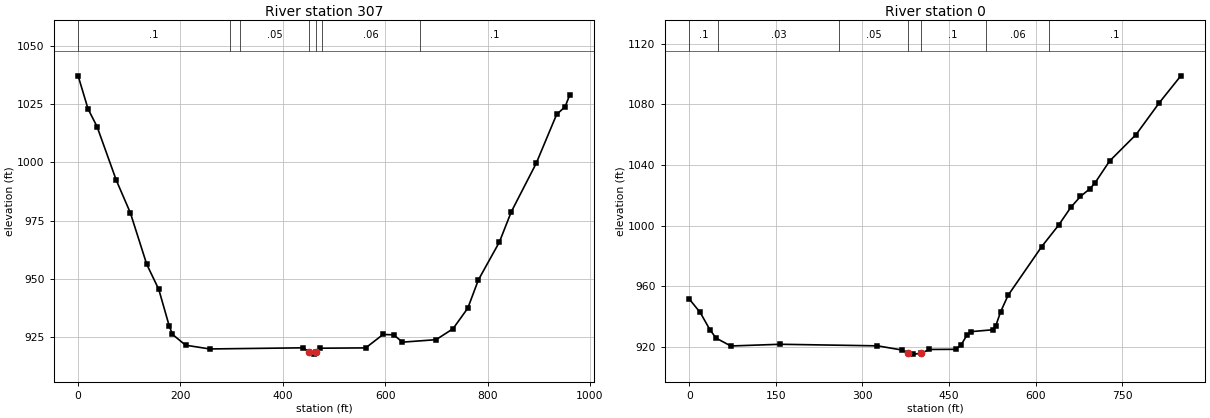
Type RM Length L Ch R = 1 ,307     ,302.8,307.4,306.2
XS GIS Cut Line= 4
 1678775.1224873384731.2647888721678865.48900401384894.117395516
1679205.22545683385125.2992751681679556.75832745385033.415640455
#Sta/Elev= 30
       0  1037.2    19.3 1023.04      37 1015.39    74.6  992.36   102.1  978.35
   134.1  956.26   157.6  945.52   178.2  929.67   184.4  926.19     210  921.56
   257.2  919.94   439.4  920.43   451.9  918.54   460.4  917.72  464.41918.5386
     472  920.26     562   920.4   595.8  926.16   616.7  926.01   633.7  922.86
   699.4  923.92   732.5  928.61   761.4  937.45   782.1  949.58   823.1  965.81
   846.4  978.82   895.2  999.68     935 1020.62   951.6 1023.93   960.5 1028.95
#Mann= 7 ,-1,0
       0      .1       0  296.24     .03       0  316.24     .05       0
   451.9    .045       0  464.41     .05       0  476.24     .06       0
  667.18      .1       0
Bank Sta=451.9,464.41
XS Rating Curve= 0 ,0
Exp/Cntr(USF)=0,0
Exp/Cntr=0.3,0.1

Type RM Length L Ch R = 1 ,0       ,,,
XS GIS Cut Line= 4
1678713.56641098384913.0828725371678817.47807282385194.701507787
 1678961.4391846385338.6599272721679064.52874707385670.669212739
#Sta/Elev= 30
       0  951.54    18.9  942.69    35.8  931.28    46.3  925.82    71.9  920.59
   157.6  921.72     326  920.68   368.4  917.93  379.41 915.654   388.2  915.22
  400.57915.6547   415.9   918.3   461.2  918.39   470.2  920.93   481.5  928.11
   487.2  930.01   526.7  931.32   530.9  933.91   539.2  943.08   552.1  953.95
   610.4  986.12   639.8 1000.32   660.8 1012.01   677.5 1019.19   694.2 1024.39
   702.6 1028.07   727.9 1042.52   773.8    1060   814.2 1081.05   851.4 1098.76
#Mann= 7 ,-1,0
       0      .1       0      50     .03       0     260     .05       0
  379.41    .045       0  400.57      .1       0  513.77     .06       0
  623.77      .1       0
Bank Sta=379.41,400.57
XS Rating Curve= 0 ,0
Exp/Cntr=0.3,0.1
LCMann Table=0

Chan Stop Cuts=-1
Use User Specified Reach Order=0
Composite Channel Slope=5